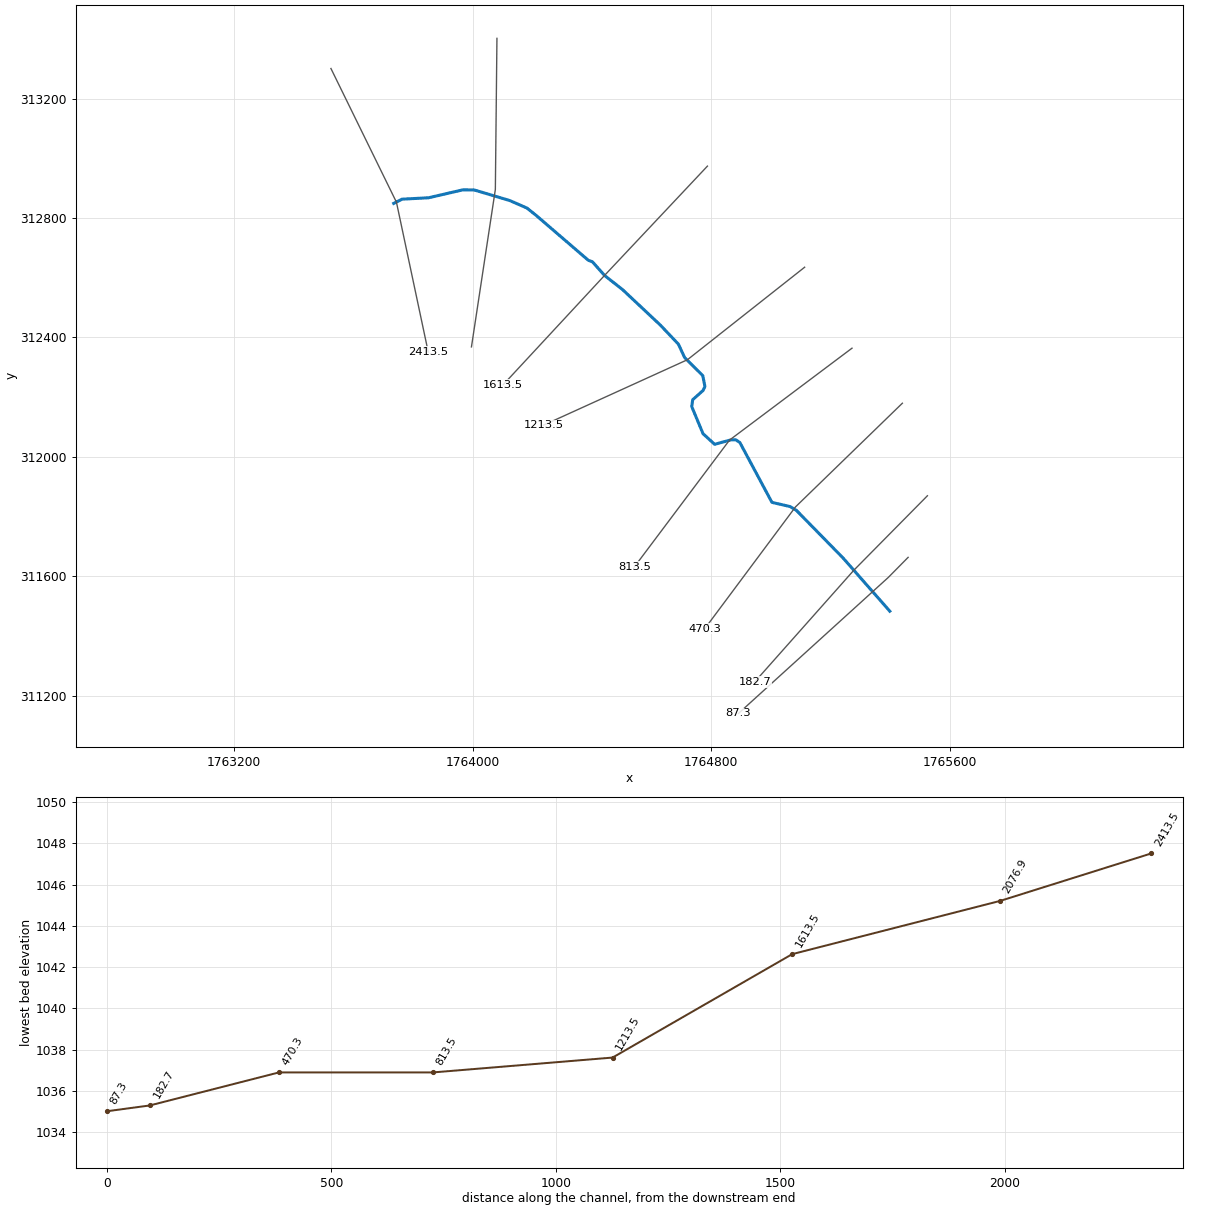
--- SgarcmpRn.prj (project) ---

Proj Title=SgarcmpRn
Current Plan=p01
Geom File=g01
Flow File=f01
Plan File=p01
DSS Export Rating Curves=0
DSS Export Rating Curve Sorted=0
DSS Export Volume Flow Curves=0
DXF OffsetX=0
DXF OffsetY=0
DXF ScaleX=0
DXF ScaleY=0

--- SgarcmpRn.p01 (plan) ---

Plan Title=Floodplain
Program Version=4.00
Geom File=g01
Flow File=f01
K Sum by GR=0
Std Step Tol=0.01
Critical Tol=0.01
Num of Std Step Trials=20
Max Error Tol=0.3
Flow Tol Ratio=0.001
Split Flow NTrial=30
Split Flow Tol=0.02
Split Flow Ratio=0.02
Log Output Level=0
Friction Slope Method=1
Unsteady Friction Slope Method=2
Unsteady Bridges Friction Slope Method=1
Global Log Level=0
CheckData=False
Run HTab=0
Run UNet=0
Run PostProcess=0
UNET Theta=0
UNET Theta Warmup=0
UNET ZTol=0
UNET ZSATol=0
UNET MxIter=0
UNET MaxInSteps=0
UNET DtIC=0
UNET DtMin=0
UNET MaxCRTS=0
UNET WFStab=0
UNET SFStab=0
UNET WFX=0
UNET SFX=0
UNET DSS MLevel=0
UNET DZMax Abort=0
UNET Convert EG Bridges=0
UNET Use Existing IB Tables=0
UNET Froude Limit=0
UNET Froude Power=0
Write IC File=0
Echo Input=False
Echo Output=False
Write Detailed=0

--- SgarcmpRn.f01 (steady flow) ---

Flow Title=NFF Regression Equation
Program Version=4.00
Number of Profiles=1
Profile Names=P100yr
River Rch & RM=SgarcmpRn,Main      ,2413.5
730.5429
River Rch & RM=SgarcmpRn,Main      ,2076.9
734.7888
River Rch & RM=SgarcmpRn,Main      ,1613.5
816.4711
River Rch & RM=SgarcmpRn,Main      ,182.7
843.7612
River Rch & RM=SgarcmpRn,Main      ,87.3
847.6105
Boundary for River Rch & Prof#=SgarcmpRn,Main      ,1
Up Type=0
Dn Type=3
Dn Slope=0.002009

--- SgarcmpRn.g01 (geometry) ---

Geom Title=USGS 3m DEM
Program Version=4.00

River Reach=SgarcmpRn     ,Main
Reach XY= 30
     1763735.938      312848.765     1763763.634      312862.972
     1763853.083      312867.697     1763967.051      312894.109
     1764005.354      312893.932     1764124.645      312858.420
     1764182.213      312833.235     1764212.316      312809.281
     1764387.939      312658.232     1764401.532      312653.280
     1764442.626      312607.104     1764502.348      312560.252
     1764629.394      312440.928     1764689.595      312377.400
     1764710.668      312332.139     1764771.407      312271.718
     1764778.556      312235.371     1764771.920      312221.761
     1764737.511      312190.965     1764734.357      312168.072
     1764772.174      312077.337     1764811.020      312041.735
     1764865.918      312056.631     1764882.010      312056.777
     1764895.654      312047.586     1765003.057      311847.204
     1765063.863      311833.141     1765084.975      311820.498
     1765241.835      311660.268     1765397.939      311482.656

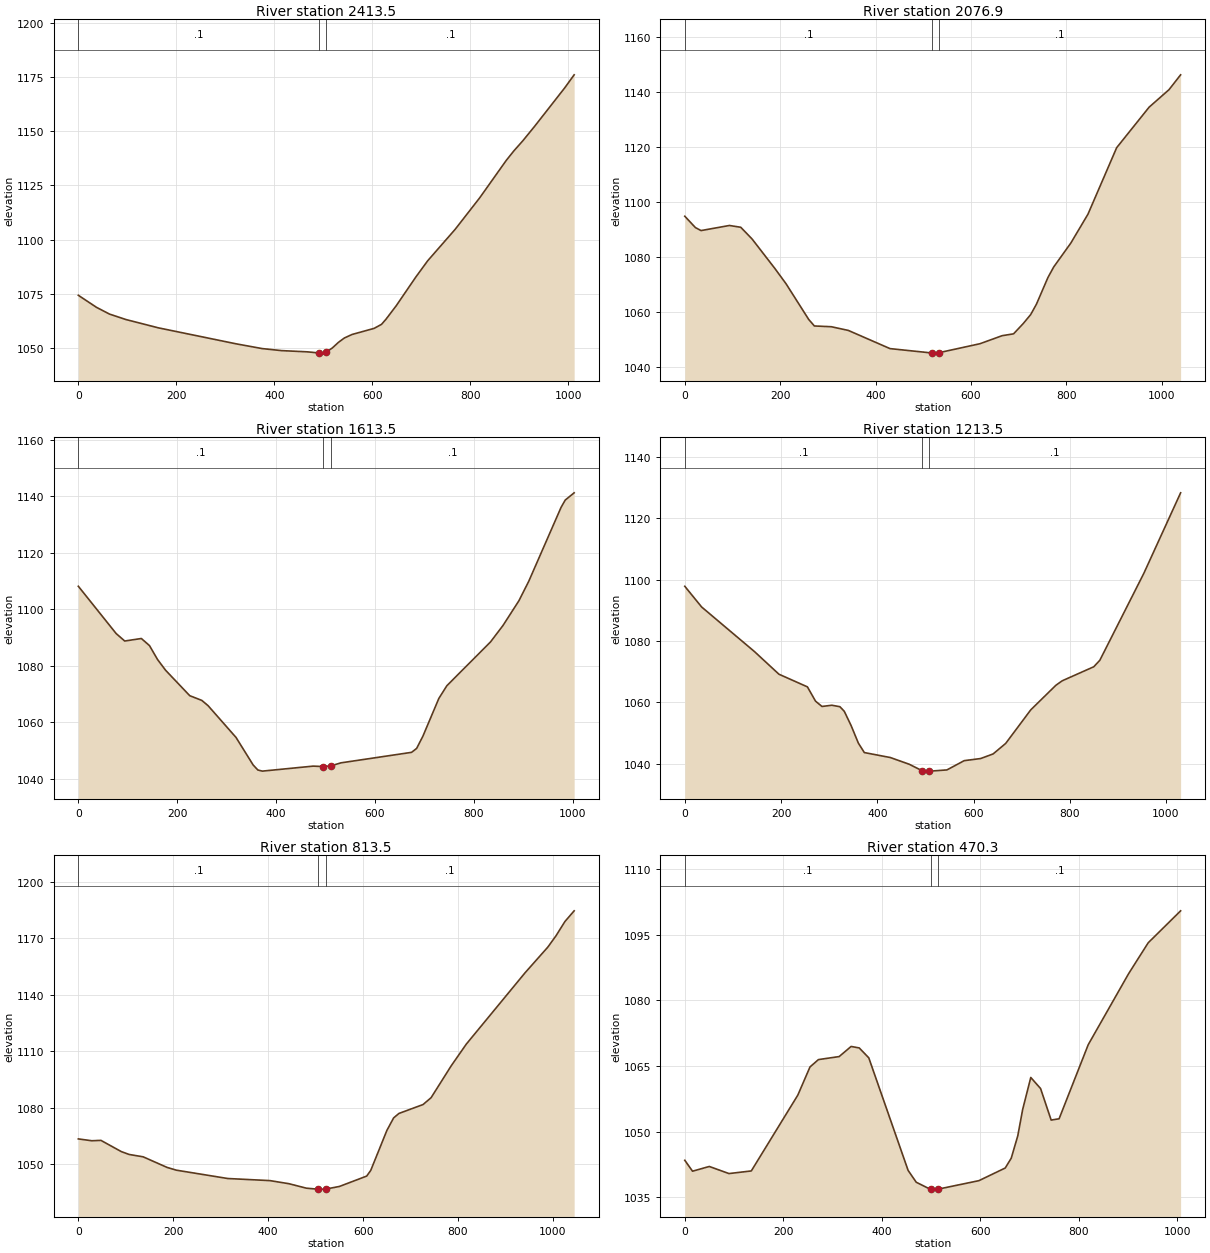
Type RM Length L Ch R = 1 ,2413.5,350.138,336.685,328.418
XS GIS Cut Line= 3
     1763525.636      313300.765     1763745.105      312852.762
     1763851.583      312350.918
#Sta/Elev= 30
       0 1074.25    37.2 1068.66    63.8 1065.54    97.4 1063.02   163.5 1059.19
   322.2 1051.80   375.1 1049.61   414.7 1048.67   467.6 1048.10   491.4 1047.58
   494.1 1047.51   506.4 1048.00   518.7 1049.97   530.9 1052.51   543.0 1054.52
   558.7 1056.14   603.7 1058.96   618.8 1060.83   628.0 1063.23   648.8 1069.44
   688.6 1082.65   712.9 1090.19   769.0 1104.74   819.0 1119.28   873.2 1136.58
   888.6 1140.95   907.1 1145.67   931.4 1152.43   992.1 1169.99  1011.8 1176.15
#Mann= 3 , 0 , 0
       0     0.1       0   491.4   0.045       0   506.4     0.1       0
Bank Sta=   491.4,   506.4
Exp/Cntr=0.3,0.1

Type RM Length L Ch R = 1 ,2076.9,477.542,463.315,449.674
XS GIS Cut Line= 3
     1764081.779      313401.812     1764076.462      312895.610
     1763996.367      312368.031
#Sta/Elev= 30
       0 1094.90    22.3 1090.78    34.1 1089.70    93.6 1091.55   117.3 1090.90
   141.1 1086.64   188.6 1076.00   212.3 1070.39   259.8 1057.44   271.7 1055.07
   307.3 1054.79   342.9 1053.45   430.3 1046.85   518.7 1045.25   525.1 1045.21
   533.7 1045.40   619.0 1048.63   665.3 1051.54   689.3 1052.21   709.5 1055.92
   725.3 1059.22   737.3 1062.98   761.4 1072.66   773.4 1076.46   809.4 1085.17
   845.4 1095.67   905.5 1119.79   973.5 1134.49  1015.2 1140.84  1039.6 1146.24
#Mann= 3 , 0 , 0
       0     0.1       0   518.7   0.045       0   533.7     0.1       0
Bank Sta=   518.7,   533.7
Exp/Cntr=0.3,0.1

Type RM Length L Ch R = 1 ,1613.5,403.269,400,390.24
XS GIS Cut Line= 3
     1764786.964      312973.717     1764442.272      312607.452
     1764102.340      312240.988
#Sta/Elev= 30
       0 1108.06    76.5 1091.32    93.8 1088.68   127.5 1089.57   143.9 1087.06
   160.2 1082.14   176.5 1078.33   225.4 1069.32   249.7 1067.67   262.4 1065.80
   319.0 1054.54   353.6 1044.80   363.1 1043.03   372.1 1042.63   474.9 1044.40
   495.5 1044.25   510.5 1044.47   531.1 1045.56   674.0 1049.28   684.2 1050.66
   696.9 1055.00   729.2 1068.38   745.4 1072.87   833.6 1088.35   858.8 1094.16
   891.2 1102.97   911.1 1109.87   976.4 1136.00   984.8 1138.58  1002.8 1141.13
#Mann= 3 , 0 , 0
       0     0.1       0   495.5   0.045       0   510.5     0.1       0
Bank Sta=   495.5,   510.5
Exp/Cntr=0.3,0.1

Type RM Length L Ch R = 1 ,1213.5,408.837,400,402.219
XS GIS Cut Line= 3
     1765112.660      312635.017     1764720.013      312325.090
     1764237.431      312105.617
#Sta/Elev= 30
       0 1097.88    35.0 1091.13   144.9 1076.58   195.6 1069.22   254.8 1065.09
   271.7 1060.43   285.1 1058.70   305.5 1059.10   322.4 1058.62   331.4 1057.13
   345.6 1052.49   360.7 1046.75   373.1 1043.67   427.2 1042.05   466.6 1039.85
   492.7 1037.80   507.7 1037.63   510.3 1037.62   544.7 1038.01   580.6 1041.03
   614.7 1041.72   640.7 1043.22   666.8 1046.64   719.0 1057.60   771.2 1065.61
   784.2 1067.06   849.9 1071.64   862.5 1073.76   953.8 1102.05  1030.4 1128.35
#Mann= 3 , 0 , 0
       0     0.1       0   492.7   0.045       0   507.7     0.1       0
Bank Sta=   492.7,   507.7
Exp/Cntr=0.3,0.1

Type RM Length L Ch R = 1 ,813.5,329.62,343.24,354.33
XS GIS Cut Line= 3
     1765271.314      312363.747     1764860.805      312055.654
     1764541.843      311630.560
#Sta/Elev= 30
       0 1063.53    28.6 1062.55    47.6 1062.76    90.4 1056.82   107.0 1055.29
   136.7 1054.02   186.9 1048.42   206.6 1046.95   314.8 1042.53   403.9 1041.41
   444.0 1039.76   480.4 1037.41   503.3 1036.90   505.8 1036.90   520.8 1036.90
   550.3 1038.33   607.6 1043.82   616.1 1046.82   650.1 1068.02   664.3 1074.66
   675.5 1077.03   726.4 1081.77   743.3 1085.40   785.7 1102.31   817.5 1113.82
   941.2 1151.61   989.3 1165.27  1006.2 1171.16  1025.3 1178.83  1044.7 1184.49
#Mann= 3 , 0 , 0
       0     0.1       0   505.8   0.045       0   520.8     0.1       0
Bank Sta=   505.8,   520.8
Exp/Cntr=0.3,0.1

Type RM Length L Ch R = 1 ,470.3,288.307,287.608,285.689
XS GIS Cut Line= 3
     1765440.101      312179.433     1765081.906      311831.860
     1764778.187      311424.180
#Sta/Elev= 30
       0 1043.48    15.7 1040.99    49.8 1042.07    89.7 1040.45   135.1 1041.05
   229.6 1058.35   254.4 1064.79   271.5 1066.46   313.6 1067.15   337.9 1069.46
   354.4 1069.12   373.8 1066.86   453.7 1041.17   470.2 1038.47   498.3 1036.90
   499.8 1036.90   514.8 1036.90   597.5 1038.83   651.0 1041.72   663.2 1043.96
   676.5 1049.08   686.4 1055.08   702.9 1062.38   722.8 1059.85   744.3 1052.66
   760.4 1052.95   819.6 1069.86   901.6 1086.06   941.4 1093.11  1007.3 1100.41
#Mann= 3 , 0 , 0
       0     0.1       0   499.8   0.045       0   514.8     0.1       0
Bank Sta=   499.8,   514.8
Exp/Cntr=0.3,0.1

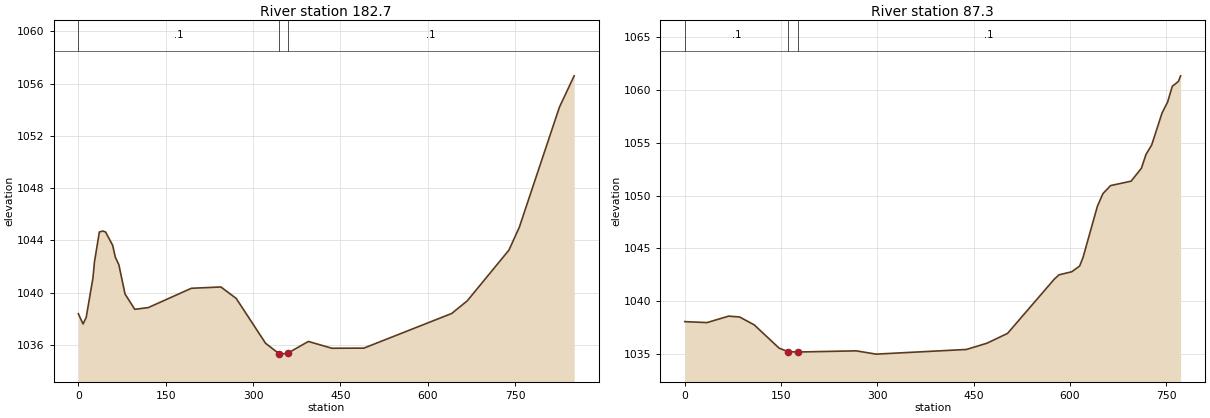
Type RM Length L Ch R = 1 ,182.7,96.665,95.378,92.933
XS GIS Cut Line= 3
     1765523.955      311869.360     1765277.394      311619.732
     1764945.170      311245.537
#Sta/Elev= 30
       0 1038.39     8.2 1037.61    13.5 1038.11    25.1 1041.12    27.7 1042.36
    36.1 1044.65    42.0 1044.72    46.8 1044.65    58.9 1043.63    63.5 1042.72
    69.6 1042.14    80.2 1039.90    96.9 1038.73   120.0 1038.86   194.1 1040.34
   244.8 1040.44   271.1 1039.56   321.5 1036.13   344.4 1035.34   346.1 1035.30
   359.4 1035.37   395.0 1036.27   435.3 1035.75   490.3 1035.76   641.0 1038.41
   667.8 1039.38   739.3 1043.26   757.2 1045.02   826.0 1054.20   851.3 1056.60
#Mann= 3 , 0 , 0
       0     0.1       0   344.4   0.045       0   359.4     0.1       0
Bank Sta=   344.4,   359.4
Exp/Cntr=0.3,0.1

Type RM Length L Ch R = 1 ,87.3,84.89,87.318,89.746
XS GIS Cut Line= 3
     1765459.351      311663.011     1765392.894      311595.694
     1764891.178      311140.277
#Sta/Elev= 30
       0 1038.09    34.6 1038.00    68.4 1038.61    85.3 1038.53   108.0 1037.79
   146.8 1035.59   161.0 1035.25     176 1035.22   266.9 1035.33   298.0 1035.02
   438.5 1035.46   470.6 1036.05   502.7 1036.98   575.4 1042.10   582.8 1042.51
   602.6 1042.80   614.9 1043.34   620.2 1044.15   642.6 1048.99   651.1 1050.17
   663.0 1050.94   695.1 1051.36   711.1 1052.58   718.3 1053.89   727.1 1054.77
   743.2 1057.79   751.9 1058.83   759.2 1060.32   768.7 1060.78   772.2 1061.31
#Mann= 3 , 0 , 0
       0     0.1       0     161   0.045       0     176     0.1       0
Bank Sta=     161,     176
Exp/Cntr=0.3,0.1